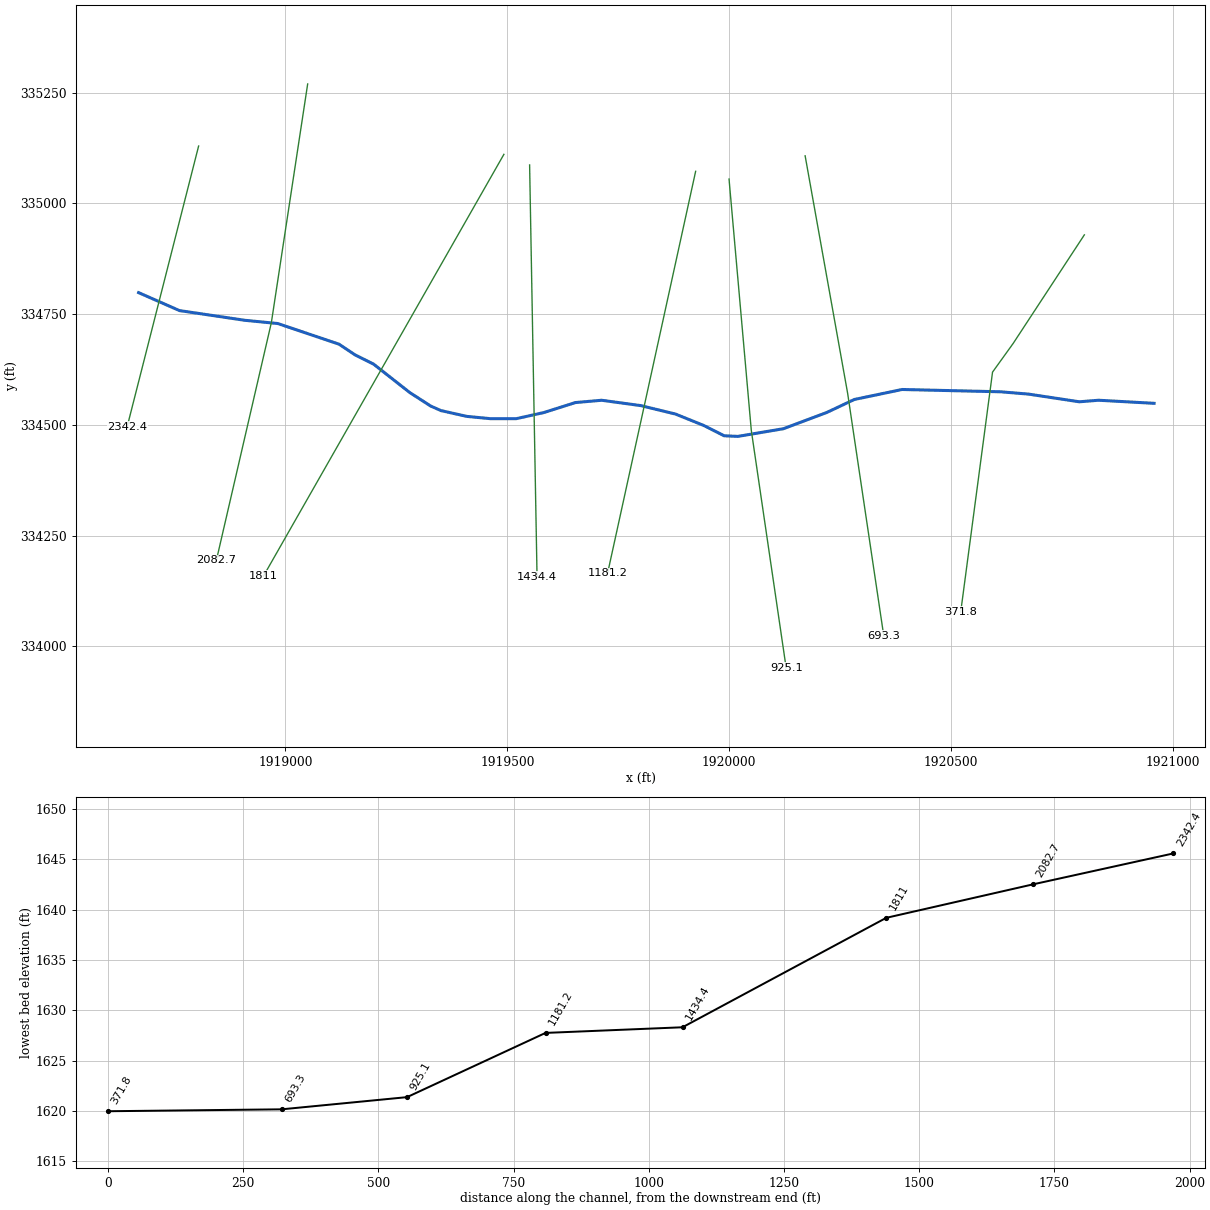
--- BendBranch.prj (project) ---

Proj Title=BendBranch
Current Plan=p01
Default Exp/Contr=0,0
English Units
Geom File=g01
Flow File=f01
Plan File=p01
BEGIN DESCRIPTION:
END DESCRIPTION:
DSS Export Rating Curves= 0
DSS Export Rating Curve Sorted= 0
DSS Export Volume Flow Curves= 0
DXF OffsetX= 0
DXF OffsetY= 0
DXF ScaleX= 0
DXF ScaleY= 0

--- BendBranch.p01 (plan) ---

Plan Title=Floodplain
Program Version=4.00
Geom File=g01
Flow File=f01
K Sum by GR=0
Std Step Tol=0.01
Critical Tol=0.01
Num of Std Step Trials=20
Max Error Tol=0.3
Flow Tol Ratio=0.001
Split Flow NTrial=30
Split Flow Tol=0.02
Split Flow Ratio=0.02
Log Output Level=0
Friction Slope Method=1
Unsteady Friction Slope Method=2
Unsteady Bridges Friction Slope Method=1
Global Log Level=0
CheckData=False
Run HTab=0
Run UNet=0
Run PostProcess=0
UNET Theta=0
UNET Theta Warmup=0
UNET ZTol=0
UNET ZSATol=0
UNET MxIter=0
UNET MaxInSteps=0
UNET DtIC=0
UNET DtMin=0
UNET MaxCRTS=0
UNET WFStab=0
UNET SFStab=0
UNET WFX=0
UNET SFX=0
UNET DSS MLevel=0
UNET DZMax Abort=0
UNET Convert EG Bridges=0
UNET Use Existing IB Tables=0
UNET Froude Limit=0
UNET Froude Power=0
Write IC File=0
Echo Input=False
Echo Output=False
Write Detailed=0

--- BendBranch.f01 (steady flow) ---

Flow Title=NFF Regression Equation
Program Version=4.10
Number of Profiles= 1
Profile Names=P100yr
River Rch & RM=BendBranch,Main            ,2342.4
516.6933
River Rch & RM=BendBranch,Main            ,2082.7
523.0968
Boundary for River Rch & Prof#=BendBranch,Main            , 1
Up Type= 0
Dn Type= 3
Dn Slope=0.0056
DSS Import GetInterval= 0
DSS Import GetPeak= 0
DSS Import FillOption= 0

--- BendBranch.g01 (geometry) ---

Geom Title=USGS 3m DEM
Program Version=4.10

River Reach=BendBranch      ,Main
Reach XY= 30
     1918669.145      334798.687     1918761.331      334758.123
     1918908.728      334736.187     1918982.793      334728.889
     1919120.534      334682.368     1919156.992      334658.062
     1919198.659      334637.229     1919280.256      334572.993
     1919327.212       334542.61     1919350.565       334532.26
     1919408.728      334519.173     1919462.548      334513.965
     1919519.839      334513.965      1919582.34      334527.854
      1919653.52      334550.423     1919712.548      334555.631
     1919801.089      334543.479     1919879.214      334524.382
      1919943.45       334498.34     1919988.556      334475.394
     1920019.839      334474.035      1920122.27      334491.395
     1920219.492      334527.854     1920281.992      334557.368
     1920389.631      334579.937     1920611.853      334574.729
     1920674.353      334569.521     1920788.937      334552.159
     1920832.339      334555.631     1920957.374      334548.679

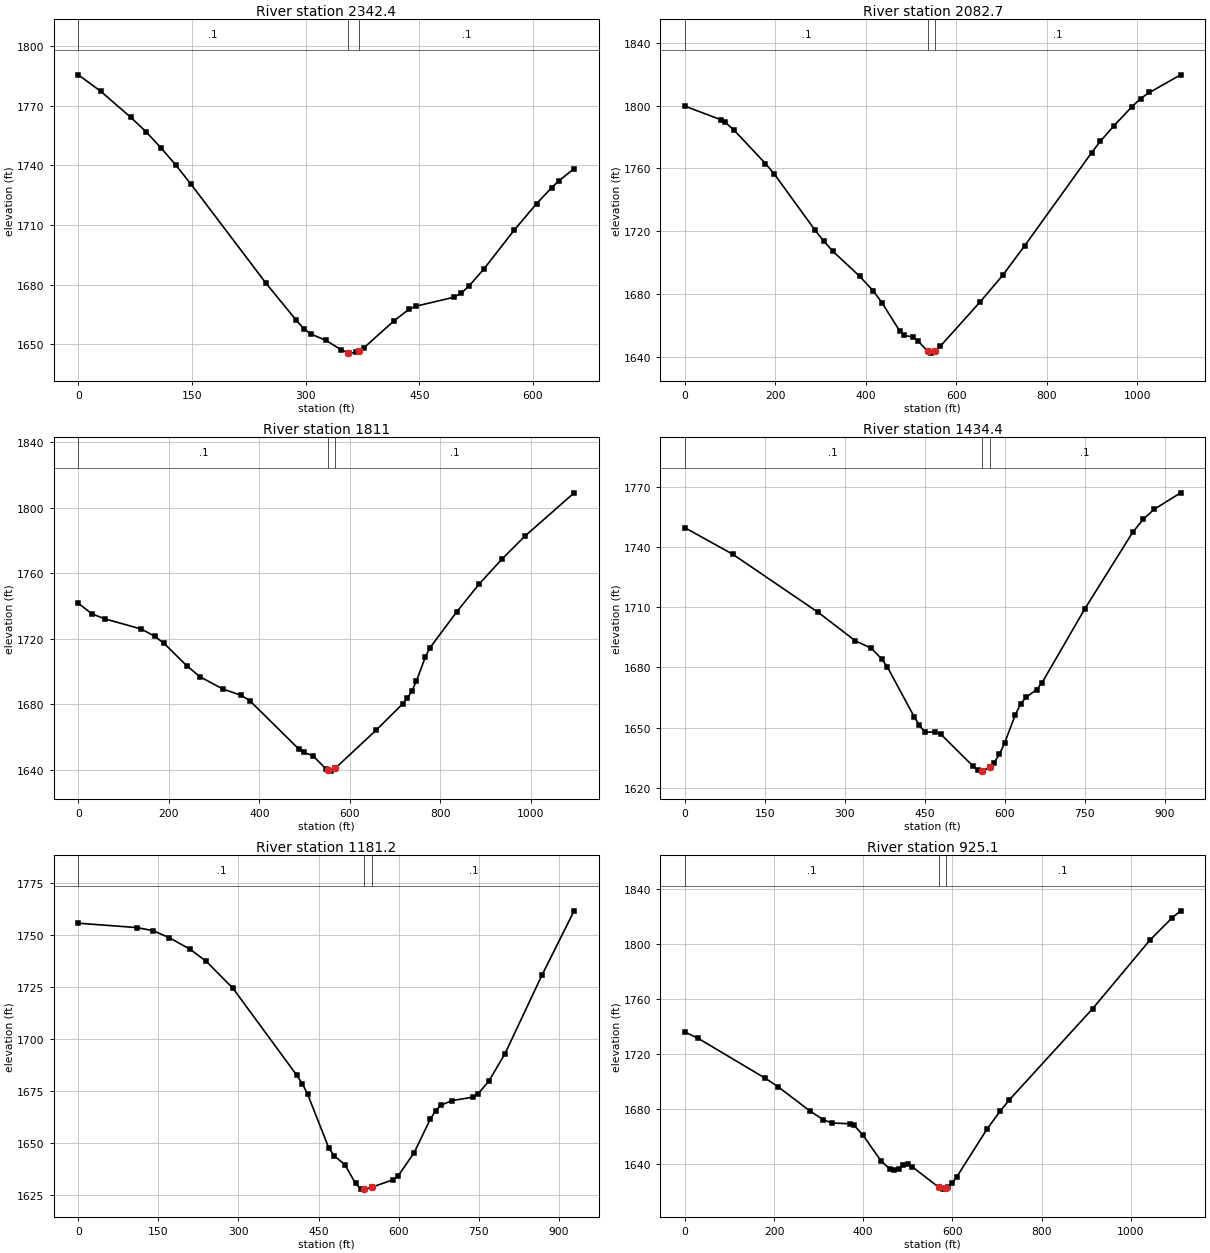
Type RM Length L Ch R = 1 ,2342.4  ,257.1,259.3,259.7
XS GIS Cut Line= 2
     1918804.416      335129.773     1918643.333      334495.638
#Sta/Elev= 30
       0 1785.42    29.7 1777.11    69.4 1763.98    89.2 1756.88     109 1748.76
   128.9 1739.96   148.7 1730.46   247.8 1680.62   287.5 1662.15   297.4  1657.9
   307.3 1655.08   327.1 1651.95     347 1647.19   355.2 1645.86   356.9 1645.58
   366.8 1645.91   370.2  1646.7   376.7  1648.2   416.4 1661.77   436.2 1667.58
   446.1 1669.21   495.7 1673.68   505.6  1675.8   515.5 1679.31   535.3  1687.9
     575 1707.31   604.7 1720.68   624.5 1728.68   634.4 1732.28   654.3 1738.24
#Mann= 3 , 0 , 0
       0      .1       0   355.2    .045       0   370.2      .1       0
Bank Sta=355.2,370.2
XS Rating Curve= 0 ,0
Exp/Cntr=0.3,0.1

Type RM Length L Ch R = 1 ,2082.7  ,279.9,271.6,265.1
XS GIS Cut Line= 3
      1919050.14      335269.983     1918968.341      334731.083
     1918844.359      334193.952
#Sta/Elev= 30
       0 1799.69    79.3 1791.05    89.2 1789.43     109 1784.37   178.4  1763.1
   198.2 1756.37   287.4 1720.93   307.2 1713.82     327 1707.44   386.5 1691.46
   416.2 1682.28   436.1 1674.55   475.7 1656.33   485.6 1653.88   505.4 1652.61
   515.3  1650.3   537.6 1643.62   545.1 1642.51   552.6  1643.6   564.8 1646.85
   653.4 1675.23   702.6 1691.91   751.8 1710.96   899.4 1770.02   919.1  1777.4
   948.7 1787.12     988 1799.13  1007.7 1804.49  1027.4 1808.35  1096.3 1819.58
#Mann= 3 , 0 , 0
       0      .1       0   537.6    .045       0   552.6      .1       0
Bank Sta=537.6,552.6
XS Rating Curve= 0 ,0
Exp/Cntr=0.3,0.1

Type RM Length L Ch R = 1 ,1811    ,364.6,376.6,388.6
XS GIS Cut Line= 2
     1919492.303      335111.005     1918950.574      334158.592
#Sta/Elev= 30
       0 1741.69    29.9 1735.19    59.8 1732.06   139.4 1725.91   169.3 1721.42
   189.3 1717.23   239.1 1703.65   268.9 1696.79   318.8 1689.37   358.6 1685.61
   378.5 1682.29   488.1 1652.42     498 1650.56     518  1648.7   547.8 1640.34
   552.7 1639.77   557.8 1639.18   567.7 1640.91   657.4 1664.01   717.2 1680.39
   727.2 1683.73   737.1 1688.12   747.1 1694.15     767 1708.98     777 1714.46
   836.7 1736.62   886.5 1753.66   936.3 1768.66   986.1 1782.46  1095.7  1809.1
#Mann= 3 , 0 , 0
       0      .1       0   552.7    .045       0   567.7      .1       0
Bank Sta=552.7,567.7
XS Rating Curve= 0 ,0
Exp/Cntr=0.3,0.1

Type RM Length L Ch R = 1 ,1434.4  ,258.4,253.2,248
XS GIS Cut Line= 2
     1919550.257      335087.015      1919567.01       334157.16
#Sta/Elev= 30
       0 1749.57      90 1736.31     250 1707.41     320 1693.18     350  1689.5
     370 1683.93     380 1680.14     430 1655.51     440  1651.1     450 1647.82
     470 1647.68     480 1646.74     540 1630.98     550 1628.67   556.6 1628.43
     560 1628.31   571.6 1630.26     580 1632.54     590 1636.61     600 1642.39
     620 1656.42     630  1661.8     640 1665.01     660 1668.96     670 1672.32
     750 1708.99     840 1747.23     860 1753.74     880 1758.64     930 1766.91
#Mann= 3 , 0 , 0
       0      .1       0   556.6    .045       0   571.6      .1       0
Bank Sta=556.6,571.6
XS Rating Curve= 0 ,0
Exp/Cntr=0.3,0.1

Type RM Length L Ch R = 1 ,1181.2  ,248.6,256,264.2
XS GIS Cut Line= 2
     1919924.369      335072.653     1919726.054      334165.316
#Sta/Elev= 30
       0  1755.7   109.8  1753.6   139.8 1752.11   169.8 1748.81   209.7  1743.1
   239.7 1737.34   289.6 1724.41   409.4 1682.46   419.4 1678.55   429.4 1673.48
   469.4 1647.41   479.4 1643.77   499.3 1639.52   519.3 1630.46   529.3 1627.75
     536 1627.77     551 1628.78   589.2 1632.23   599.2 1634.14   629.2 1645.37
   659.1  1661.3   669.1 1665.47   679.1 1668.06   699.1  1670.3     739 1672.01
     749 1673.68     769 1679.74   798.9 1692.75   868.8 1730.87   928.8 1761.66
#Mann= 3 , 0 , 0
       0      .1       0     536    .045       0     551      .1       0
Bank Sta=536,551
XS Rating Curve= 0 ,0
Exp/Cntr=0.3,0.1

Type RM Length L Ch R = 1 ,925.1   ,231,231.7,231.6
XS GIS Cut Line= 3
     1919999.623      335055.269     1920049.786      334487.687
     1920128.296      333951.461
#Sta/Elev= 30
       0  1735.7      30 1731.07   179.9 1702.16   209.9  1695.7   279.9 1678.36
   309.9 1672.01   329.9 1669.47   369.9 1668.96   379.9 1667.69   399.9 1660.45
   439.8 1641.98   459.8 1636.01   469.8  1635.1   479.8 1636.23   489.8 1638.73
   499.8  1639.3   509.8 1637.68   569.8 1622.59   579.6 1621.37   584.8 1622.06
   589.5 1622.69   599.4 1625.82   609.2 1629.99   678.2 1665.34   707.7 1678.41
   727.4 1686.22   914.7  1752.8  1042.8 1802.54    1092  1818.6  1111.7 1823.87
#Mann= 3 , 0 , 0
       0      .1       0   569.8    .045       0   584.8      .1       0
Bank Sta=569.8,584.8
XS Rating Curve= 0 ,0
Exp/Cntr=0.3,0.1

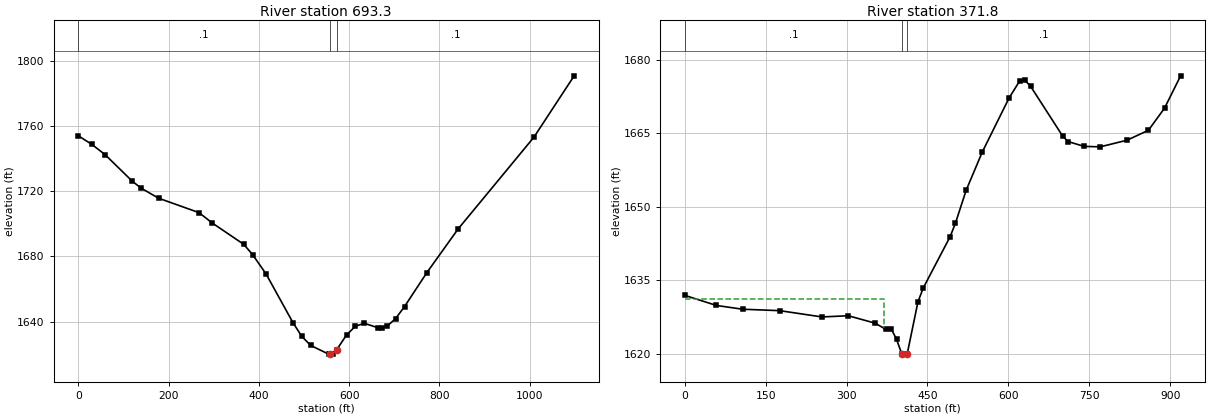
Type RM Length L Ch R = 1 ,693.3   ,327.7,321.5,315.3
XS GIS Cut Line= 3
     1920171.097       335107.71     1920266.838      334571.555
     1920348.241      334023.841
#Sta/Elev= 30
       0 1753.95    29.7 1748.72    59.4 1742.37   118.8  1726.3   138.6 1721.93
   178.2 1715.65   267.4 1706.86   297.1 1700.42   366.4 1687.45   386.2 1681.09
   415.9 1669.27   475.3 1639.54   495.1 1630.97   514.9 1625.47   554.5 1620.16
   557.3 1620.25   564.4 1620.48   572.3 1622.82   594.1 1631.89   613.8 1637.27
   633.6 1639.05   663.3 1636.36   673.2 1636.22   683.1 1637.09   702.8 1641.92
   722.6 1649.29   772.1 1670.11   841.3 1696.85  1009.4 1753.14  1098.4 1790.69
#Mann= 3 , 0 , 0
       0      .1       0   557.3    .045       0   572.3      .1       0
Bank Sta=557.3,572.3
XS Rating Curve= 0 ,0
Exp/Cntr=0.3,0.1

Type RM Length L Ch R = 1 ,371.8   ,369.9,371.7,373.4
XS GIS Cut Line= 4
     1920800.283      334929.149      1920639.71      334683.702
     1920593.391      334619.202     1920521.656      334077.293
#Sta/Elev= 30
       0 1631.96    58.7  1629.9   107.6 1629.13     176 1628.84   254.2 1627.56
   303.2  1627.8   352.9 1626.29   372.7 1625.03   382.6 1625.17   392.6    1623
   402.5 1619.97   412.5 1620.06   432.4 1630.67   442.3  1633.5     492 1643.94
   501.9 1646.71   521.8 1653.43   551.6 1661.21   601.3 1672.24   621.2 1675.76
   631.1 1675.81   641.1 1674.64   700.7 1664.46   710.6 1663.35   740.4 1662.36
   770.3 1662.27     820 1663.62   859.7 1665.65   889.5 1670.15   919.4 1676.76
#Mann= 3 , 0 , 0
       0      .1       0   402.5    .045       0   412.5      .1       0
#XS Ineff= 2 , 0
             370 1631.17
Permanent Ineff=
       F       F
Bank Sta=402.5,412.5
XS Rating Curve= 0 ,0
Exp/Cntr=0.3,0.1

Chan Stop Cuts=-1
Use User Specified Reach Order=0
Composite Channel Slope=5